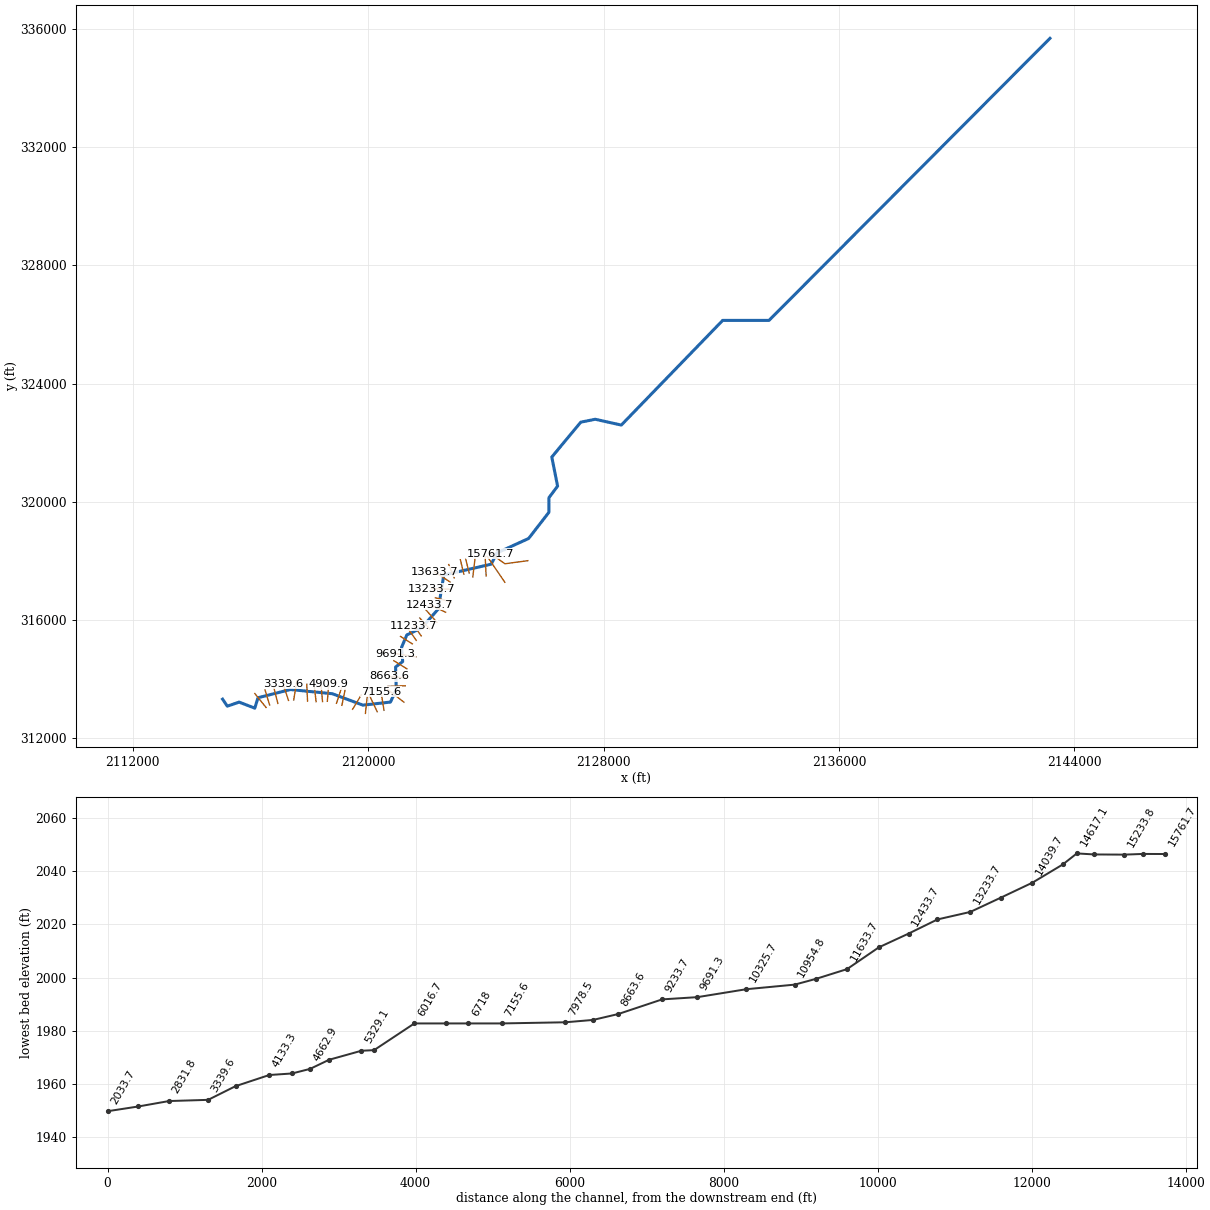
--- MlgnCkT3.prj (project) ---

Proj Title=MlgnCkT3
Current Plan=p01
Default Exp/Contr=0,0
English Units
Geom File=g01
Flow File=f01
Plan File=p01
BEGIN DESCRIPTION:
END DESCRIPTION:
DSS Export Rating Curves= 0
DSS Export Rating Curve Sorted= 0
DSS Export Volume Flow Curves= 0
DXF OffsetX= 0
DXF OffsetY= 0
DXF ScaleX= 0
DXF ScaleY= 0

--- MlgnCkT3.p01 (plan) ---

Plan Title=Floodplain
Program Version=4.00
Geom File=g01
Flow File=f01
K Sum by GR=0
Std Step Tol=0.01
Critical Tol=0.01
Num of Std Step Trials=20
Max Error Tol=0.3
Flow Tol Ratio=0.001
Split Flow NTrial=30
Split Flow Tol=0.02
Split Flow Ratio=0.02
Log Output Level=0
Friction Slope Method=1
Unsteady Friction Slope Method=2
Unsteady Bridges Friction Slope Method=1
Global Log Level=0
CheckData=False
Run HTab=0
Run UNet=0
Run PostProcess=0
UNET Theta=0
UNET Theta Warmup=0
UNET ZTol=0
UNET ZSATol=0
UNET MxIter=0
UNET MaxInSteps=0
UNET DtIC=0
UNET DtMin=0
UNET MaxCRTS=0
UNET WFStab=0
UNET SFStab=0
UNET WFX=0
UNET SFX=0
UNET DSS MLevel=0
UNET DZMax Abort=0
UNET Convert EG Bridges=0
UNET Use Existing IB Tables=0
UNET Froude Limit=0
UNET Froude Power=0
Write IC File=0
Echo Input=False
Echo Output=False
Write Detailed=0

--- MlgnCkT3.f01 (steady flow) ---

Flow Title=NFF Regression Equation
Program Version=4.00
Number of Profiles=1
Profile Names=P100yr
River Rch & RM=MlgnCkT3,Main      ,15761.7
964.5964
River Rch & RM=MlgnCkT3,Main      ,15761.7
1019.084
River Rch & RM=MlgnCkT3,Main      ,15761.7
1137.859
River Rch & RM=MlgnCkT3,Main      ,15761.7
1146.342
River Rch & RM=MlgnCkT3,Main      ,15761.7
1273.458
River Rch & RM=MlgnCkT3,Main      ,15761.7
1421.618
River Rch & RM=MlgnCkT3,Main      ,15761.7
1507.719
River Rch & RM=MlgnCkT3,Main      ,15761.7
1674.836
River Rch & RM=MlgnCkT3,Main      ,15761.7
1944.078
River Rch & RM=MlgnCkT3,Main      ,15472.6
2123.284
River Rch & RM=MlgnCkT3,Main      ,15233.8
2483.568
River Rch & RM=MlgnCkT3,Main      ,12433.7
2573.980
River Rch & RM=MlgnCkT3,Main      ,43.3
2840.647
Boundary for River Rch & Prof#=MlgnCkT3,Main      ,1
Up Type=0
Dn Type=3
Dn Slope=0.010012

--- MlgnCkT3.g01 (geometry) ---

Geom Title=USGS 10m DEM
Program Version=4.00

River Reach=MlgnCkT3     ,Main
Reach XY= 30
     2143171.083      335683.669     2133623.955      326136.541
     2132049.171      326136.541     2128604.331      322593.277
     2127718.515      322790.125     2127226.395      322691.701
     2126242.155      321510.613     2126439.003      320526.373
     2126143.731      320132.677     2126143.731      319640.557
     2125454.763      318754.741     2124372.099      318262.621
     2124185.709      317885.904     2122572.220      317517.170
     2122384.720      316370.035     2121817.011      315725.504
     2121315.709      315489.827     2121137.324      315071.858
     2121175.084      314587.483     2120934.199      314403.889
     2120955.032      313636.962     2120759.720      313217.691
     2119823.522      313113.525     2118781.855      313500.243
     2117357.376      313642.170     2116257.115      313363.525
     2116149.043      313011.962     2115616.490      313216.389
     2115214.147      313078.368     2115054.245      313315.586

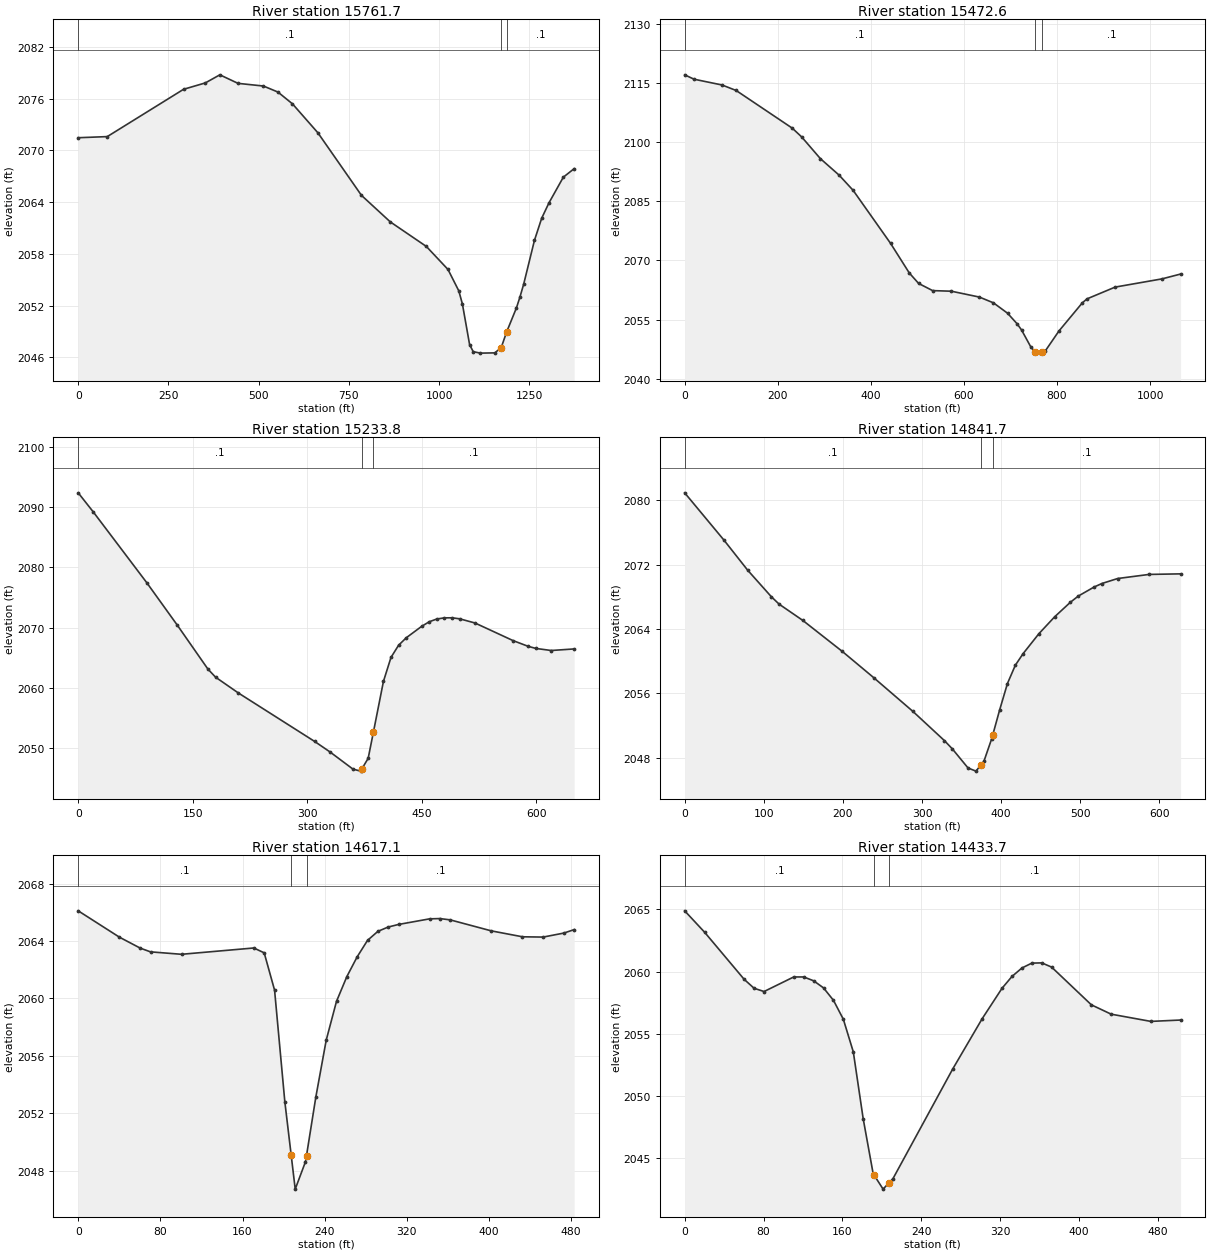
Type RM Length L Ch R = 1 ,15761.7,299.6,289.1,280.5
XS GIS Cut Line= 3
     2125426.630      318003.316     2124648.909      317898.697
     2124169.458      318241.064
#Sta/Elev= 30
       0 2071.48    80.5 2071.61   291.8 2077.10   352.1 2077.84   392.4 2078.78
   442.7 2077.79   513.1 2077.48   553.3 2076.78   593.6 2075.41   664.0 2072.05
   784.7 2064.79   864.6 2061.71   964.5 2058.86  1024.4 2056.19  1054.3 2053.71
  1064.3 2052.19  1084.3 2047.46  1094.3 2046.65  1114.2 2046.48  1154.2 2046.51
  1171.9 2047.13  1186.9 2048.94  1214.1 2051.74  1224.1 2053.04  1234.1 2054.49
  1264.0 2059.58  1284.0 2062.14  1304.0 2063.91  1343.9 2066.90  1373.9 2067.89
#Mann= 3 , 0 , 0
       0     0.1       0  1171.9   0.045       0  1186.9     0.1       0
Bank Sta=  1171.9,  1186.9
Exp/Cntr=0.3,0.1

Type RM Length L Ch R = 1 ,15472.6,250.1,238.8,227.2
XS GIS Cut Line= 2
     2124645.998      317272.090     2124044.952      318151.866
#Sta/Elev= 30
       0 2117.03    20.1 2115.92    80.4 2114.45   110.6 2113.06   231.2 2103.51
   251.3 2101.30   291.5 2095.80   331.7 2091.62   361.9 2087.76   442.3 2074.33
   482.5 2066.83   502.6 2064.17   532.7 2062.35   573.0 2062.20   633.3 2060.71
   663.4 2059.25   693.6 2056.63   713.7 2054.01   723.7 2052.39   743.8 2048.05
   753.3 2046.75   763.9 2046.51   768.3 2046.69   774.0 2046.94   804.1 2052.12
   854.4 2059.26   864.4 2060.26   924.8 2063.24  1025.3 2065.32  1065.5 2066.55
#Mann= 3 , 0 , 0
       0     0.1       0   753.3   0.045       0   768.3     0.1       0
Bank Sta=   753.3,   768.3
Exp/Cntr=0.3,0.1

Type RM Length L Ch R = 1 ,15233.8,396.2,392.2,388.1
XS GIS Cut Line= 2
     2124011.271      317483.460     2123977.466      318132.173
#Sta/Elev= 30
       0 2092.37    20.0 2089.16    89.9 2077.46   129.9 2070.42   169.9 2063.16
   179.9 2061.82   209.9 2059.19   309.8 2051.16   329.8 2049.43   359.8 2046.59
   369.8 2046.25   371.7 2046.66   379.8 2048.37   386.7 2052.74   399.8 2061.12
   409.7 2065.10   419.7 2067.12   429.7 2068.35   449.7 2070.23   459.7 2071.00
   469.7 2071.46   479.7 2071.65   489.7 2071.66   499.7 2071.49   519.7 2070.80
   569.6 2067.88   589.6 2066.92   599.6 2066.58   619.6 2066.24   649.6 2066.50
#Mann= 3 , 0 , 0
       0     0.1       0   371.7   0.045       0   386.7     0.1       0
Bank Sta=   371.7,   386.7
Exp/Cntr=0.3,0.1

Type RM Length L Ch R = 1 ,14841.7,216.2,224.6,233
XS GIS Cut Line= 2
     2123558.269      317452.890     2123632.234      318075.448
#Sta/Elev= 30
       0 2080.94    49.8 2075.04    79.6 2071.32   109.5 2068.02   119.4 2067.09
   149.3 2065.07   199.0 2061.23   238.8 2057.96   288.6 2053.74   328.4 2050.11
   338.4 2049.08   358.2 2046.71   368.2 2046.32   374.4 2047.08   378.2 2047.53
   388.1 2050.35   389.4 2050.81   398.1 2053.92   408.0 2057.22   418.0 2059.50
   427.9 2060.95   447.8 2063.42   467.7 2065.52   487.6 2067.33   497.6 2068.10
   517.5 2069.22   527.4 2069.66   547.3 2070.28   587.1 2070.79   626.9 2070.86
#Mann= 3 , 0 , 0
       0     0.1       0   374.4   0.045       0   389.4     0.1       0
Bank Sta=   374.4,   389.4
Exp/Cntr=0.3,0.1

Type RM Length L Ch R = 1 ,14617.1,183.5,183.3,183.2
XS GIS Cut Line= 2
     2123434.341      317583.545     2123317.527      318052.128
#Sta/Elev= 30
       0 2066.11    40.2 2064.27    60.4 2063.51    70.4 2063.25   100.6 2063.08
   171.0 2063.52   181.1 2063.18   191.2 2060.58   201.2 2052.79   207.3 2049.12
   211.3 2046.71   221.3 2048.62   222.3 2049.05   231.4 2053.14   241.5 2057.10
   251.5 2059.80   261.6 2061.53   271.6 2062.90   281.7 2064.05   291.8 2064.68
   301.8 2064.98   311.9 2065.16   342.1 2065.55   352.1 2065.57   362.2 2065.48
   402.4 2064.71   432.6 2064.30   452.7 2064.28   472.9 2064.56   482.9 2064.80
#Mann= 3 , 0 , 0
       0     0.1       0   207.3   0.045       0   222.3     0.1       0
Bank Sta=   207.3,   222.3
Exp/Cntr=0.3,0.1

Type RM Length L Ch R = 1 ,14433.7,389.8,394,402
XS GIS Cut Line= 2
     2123253.744      317546.851     2123134.730      318035.438
#Sta/Elev= 30
       0 2064.89    20.1 2063.18    60.3 2059.39    70.4 2058.67    80.5 2058.41
   110.6 2059.58   120.7 2059.58   130.8 2059.27   140.8 2058.70   150.9 2057.70
   160.9 2056.18   171.0 2053.56   181.0 2048.20   191.1 2043.79   192.2 2043.65
   201.2 2042.54   207.2 2043.05   211.2 2043.38   271.6 2052.16   301.7 2056.23
   321.8 2058.67   331.9 2059.62   342.0 2060.30   352.0 2060.69   362.1 2060.71
   372.1 2060.37   412.4 2057.34   432.5 2056.59   472.7 2056.01   502.9 2056.12
#Mann= 3 , 0 , 0
       0     0.1       0   192.2   0.045       0   207.2     0.1       0
Bank Sta=   192.2,   207.2
Exp/Cntr=0.3,0.1

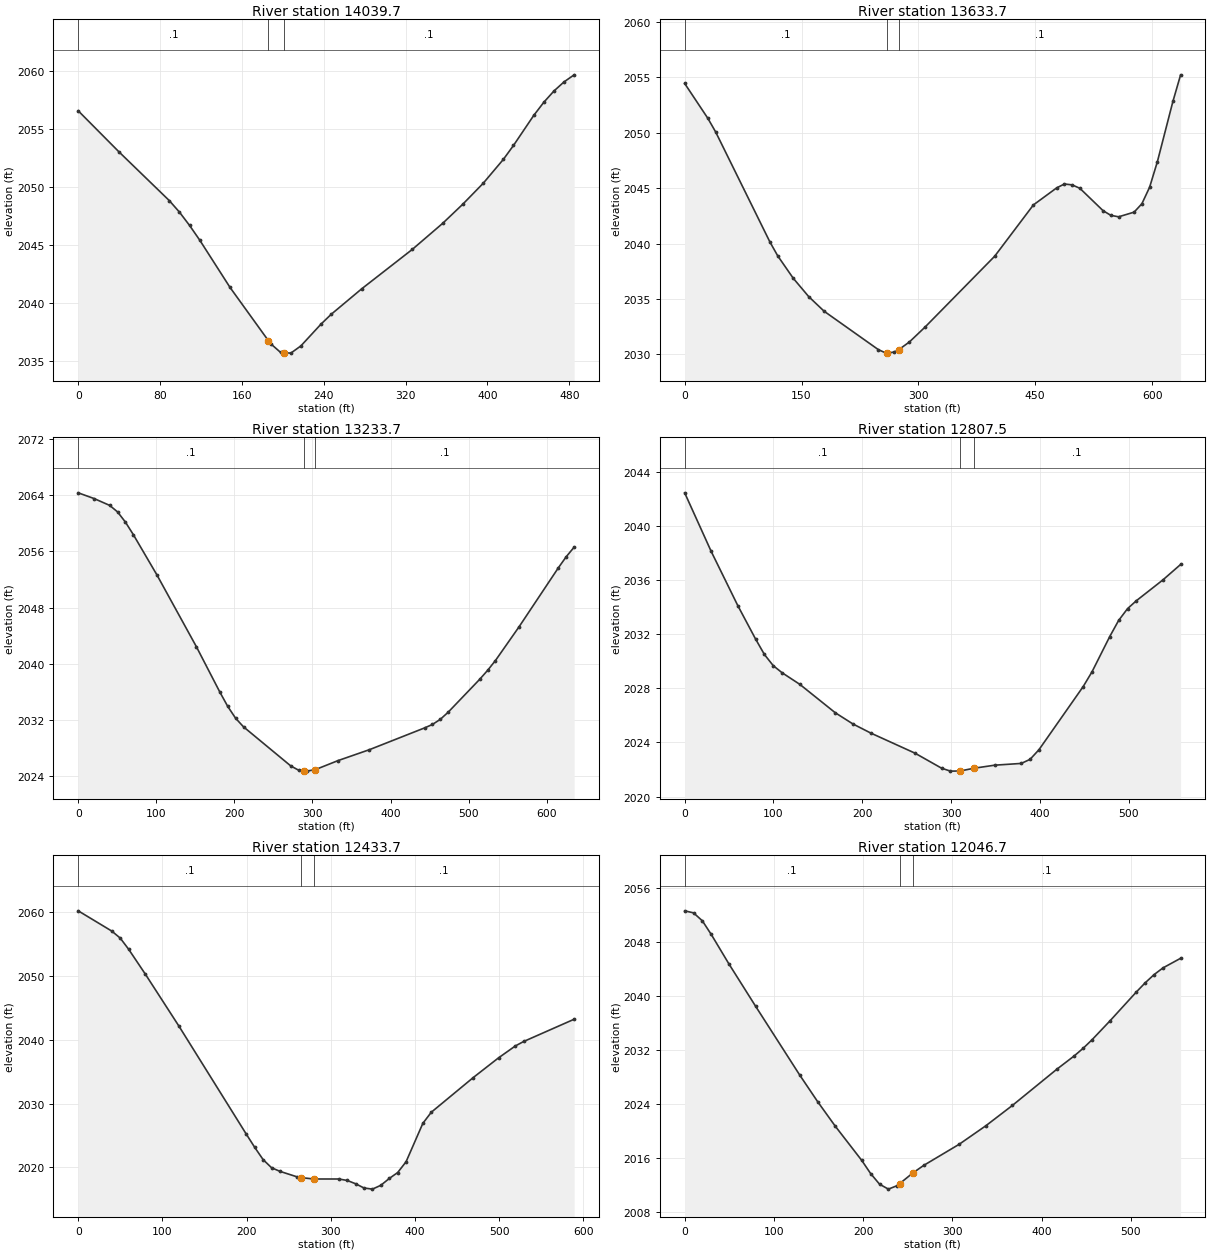
Type RM Length L Ch R = 1 ,14039.7,393.6,406,414.5
XS GIS Cut Line= 2
     2122925.012      317423.860     2122738.789      317871.404
#Sta/Elev= 27
       0 2056.59    39.6 2053.07    89.0 2048.85    98.9 2047.86   108.8 2046.71
   118.7 2045.45   148.4 2041.36   185.9 2036.77   188.0 2036.52   197.8 2035.76
   200.9 2035.74   207.8 2035.70   217.6 2036.32   237.4 2038.21   247.3 2039.05
   277.0 2041.24   326.5 2044.64   356.1 2046.88   375.9 2048.54   395.7 2050.33
   415.5 2052.40   425.4 2053.60   445.2 2056.19   455.1 2057.33   465.0 2058.30
   474.8 2059.08   484.7 2059.69
#Mann= 3 , 0 , 0
       0     0.1       0   185.9   0.045       0   200.9     0.1       0
Bank Sta=   185.9,   200.9
Exp/Cntr=0.3,0.1

Type RM Length L Ch R = 1 ,13633.7,386,400,417.1
XS GIS Cut Line= 2
     2122783.668      317284.657     2122250.863      317633.074
#Sta/Elev= 30
       0 2054.45    29.8 2051.30    39.8 2050.07   109.4 2040.15   119.4 2038.90
   139.3 2036.88   159.2 2035.22   179.0 2033.90   248.7 2030.43   258.6 2030.12
   259.8 2030.13   268.6 2030.21   274.8 2030.43   288.5 2031.13   308.4 2032.46
   397.9 2038.86   447.6 2043.49   477.5 2045.03   487.4 2045.38   497.4 2045.30
   507.3 2044.99   537.1 2042.97   547.1 2042.55   557.0 2042.42   576.9 2042.84
   586.9 2043.60   596.8 2045.09   606.8 2047.40   626.7 2052.83   636.6 2055.23
#Mann= 3 , 0 , 0
       0     0.1       0   259.8   0.045       0   274.8     0.1       0
Bank Sta=   259.8,   274.8
Exp/Cntr=0.3,0.1

Type RM Length L Ch R = 1 ,13233.7,431.6,426.3,417.3
XS GIS Cut Line= 2
     2122795.683      317036.213     2122161.027      317059.810
#Sta/Elev= 30
       0 2064.36    20.2 2063.55    40.3 2062.57    50.4 2061.64    60.5 2060.18
    70.6 2058.40   100.8 2052.66   151.2 2042.46   181.5 2035.94   191.5 2033.92
   201.6 2032.23   211.7 2031.01   272.2 2025.44   282.3 2024.83   288.6 2024.75
   292.4 2024.70   303.6 2024.91   332.7 2026.20   373.0 2027.76   443.6 2030.86
   453.6 2031.35   463.7 2032.08   473.8 2033.10   514.1 2037.78   524.2 2039.05
   534.3 2040.46   564.5 2045.26   614.9 2053.68   625.0 2055.26   635.1 2056.62
#Mann= 3 , 0 , 0
       0     0.1       0   288.6   0.045       0   303.6     0.1       0
Bank Sta=   288.6,   303.6
Exp/Cntr=0.3,0.1

Type RM Length L Ch R = 1 ,12807.5,378.3,373.7,366.3
XS GIS Cut Line= 2
     2122825.243      316603.591     2122285.865      316749.009
#Sta/Elev= 28
       0 2042.47    29.9 2038.13    59.8 2034.13    79.8 2031.66    89.8 2030.51
    99.8 2029.68   109.7 2029.16   129.7 2028.30   169.6 2026.20   189.5 2025.37
   209.5 2024.70   259.4 2023.21   289.3 2022.10   299.3 2021.88   310.4 2021.89
   325.4 2022.09   349.2 2022.32   379.1 2022.45   389.0 2022.75   399.0 2023.46
   448.9 2028.14   458.9 2029.24   478.8 2031.84   488.8 2033.03   498.8 2033.90
   508.8 2034.49   538.7 2036.03   558.6 2037.17
#Mann= 3 , 0 , 0
       0     0.1       0   310.4   0.045       0   325.4     0.1       0
Bank Sta=   310.4,   325.4
Exp/Cntr=0.3,0.1

Type RM Length L Ch R = 1 ,12433.7,396,387,374.4
XS GIS Cut Line= 2
     2122633.228      316258.522     2122099.497      316507.721
#Sta/Elev= 30
       0 2060.24    39.9 2057.06    49.9 2055.96    59.9 2054.21    79.9 2050.27
   119.8 2042.11   199.7 2025.18   209.7 2023.11   219.6 2021.20   229.6 2019.93
   239.6 2019.36   259.6 2018.51   264.9 2018.37   279.9 2018.16   309.5 2018.16
   319.5 2017.93   329.5 2017.41   339.4 2016.75   349.4 2016.57   359.4 2017.17
   369.4 2018.24   379.4 2019.17   389.4 2020.87   409.3 2026.89   419.3 2028.63
   469.2 2034.08   499.2 2037.17   519.2 2039.04   529.1 2039.74   589.0 2043.23
#Mann= 3 , 0 , 0
       0     0.1       0   264.9   0.045       0   279.9     0.1       0
Bank Sta=   264.9,   279.9
Exp/Cntr=0.3,0.1

Type RM Length L Ch R = 1 ,12046.7,416.9,413,406.3
XS GIS Cut Line= 2
     2122336.583      315920.596     2121965.972      316334.848
#Sta/Elev= 30
       0 2052.68     9.9 2052.38    19.8 2051.20    29.8 2049.17    49.6 2044.80
    79.4 2038.54   129.0 2028.30   148.9 2024.39   168.7 2020.74   198.5 2015.64
   208.4 2013.70   218.4 2012.12   228.3 2011.39   238.2 2011.91   240.8 2012.19
   255.8 2013.80   268.0 2014.92   307.7 2018.05   337.5 2020.79   367.2 2023.80
   416.9 2029.16   436.7 2031.17   446.7 2032.30   456.6 2033.56   476.4 2036.32
   506.2 2040.64   516.1 2042.00   526.1 2043.22   536.0 2044.21   555.8 2045.64
#Mann= 3 , 0 , 0
       0     0.1       0   240.8   0.045       0   255.8     0.1       0
Bank Sta=   240.8,   255.8
Exp/Cntr=0.3,0.1

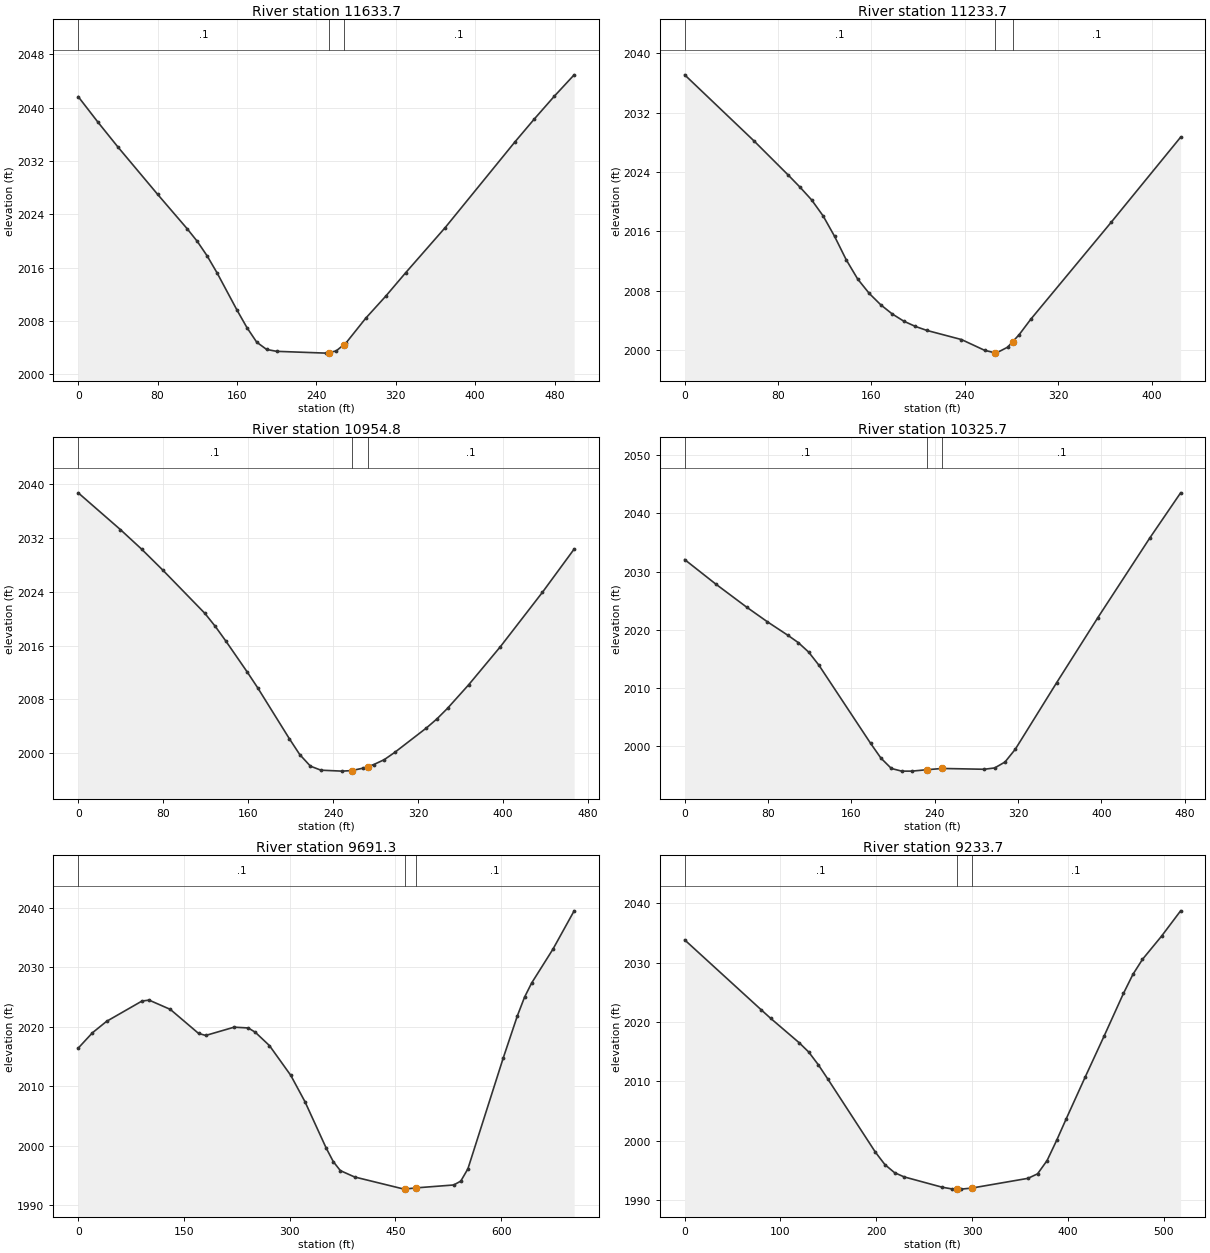
Type RM Length L Ch R = 1 ,11633.7,400.2,400,398.8
XS GIS Cut Line= 2
     2122091.009      315692.222     2121756.455      316063.590
#Sta/Elev= 26
       0 2041.67    20.0 2037.82    40.0 2034.12    80.0 2027.02   110.0 2021.82
   120.0 2019.96   130.0 2017.77   140.0 2015.22   160.0 2009.66   170.0 2007.04
   179.9 2004.84   189.9 2003.75   199.9 2003.47   249.9 2003.20   252.4 2003.28
   259.9 2003.52   267.4 2004.43   269.9 2004.73   289.9 2008.46   309.9 2011.74
   329.9 2015.24   369.9 2022.04   439.9 2034.84   459.8 2038.34   479.8 2041.73
   499.8 2044.94
#Mann= 3 , 0 , 0
       0     0.1       0   252.4   0.045       0   267.4     0.1       0
Bank Sta=   252.4,   267.4
Exp/Cntr=0.3,0.1

Type RM Length L Ch R = 1 ,11233.7,280.3,279,273.2
XS GIS Cut Line= 2
     2121802.214      315459.339     2121558.475      315807.268
#Sta/Elev= 25
       0 2037.09    59.3 2028.19    88.9 2023.54    98.8 2021.94   108.7 2020.23
   118.6 2018.06   128.4 2015.31   138.3 2012.17   148.2 2009.55   158.1 2007.61
   168.0 2006.07   177.8 2004.84   187.7 2003.87   197.6 2003.16   207.5 2002.62
   237.1 2001.39   256.9 1999.94     266 1999.59   266.7 1999.56   276.6 2000.36
     281 2001.11   286.5 2002.05   296.4 2004.12   365.5 2017.24   424.8 2028.68
#Mann= 3 , 0 , 0
       0     0.1       0     266   0.045       0     281     0.1       0
Bank Sta=     266,     281
Exp/Cntr=0.3,0.1

Type RM Length L Ch R = 1 ,10954.8,380.3,629.1,391.3
XS GIS Cut Line= 2
     2121634.731      315307.082     2121366.840      315689.487
#Sta/Elev= 27
       0 2038.65    39.7 2033.20    59.6 2030.31    79.5 2027.21   119.2 2020.78
   129.1 2018.83   139.1 2016.64   159.0 2012.10   168.9 2009.75   198.7 2002.20
   208.6 1999.82   218.6 1998.11   228.5 1997.51   248.4 1997.37   257.4 1997.45
   268.2 1997.81   272.4 1998.03   278.2 1998.34   288.1 1999.07   298.0 2000.15
   327.8 2003.77   337.8 2005.13   347.7 2006.69   367.6 2010.18   397.4 2015.82
   437.1 2023.91   466.9 2030.31
#Mann= 3 , 0 , 0
       0     0.1       0   257.4   0.045       0   272.4     0.1       0
Bank Sta=   257.4,   272.4
Exp/Cntr=0.3,0.1

Type RM Length L Ch R = 1 ,10325.7,609,634.4,648
XS GIS Cut Line= 2
     2121502.942      315186.859     2121099.356      315439.401
#Sta/Elev= 23
       0 2032.06    29.8 2027.85    59.5 2023.87    79.4 2021.35    99.2 2019.01
   109.1 2017.76   119.0 2016.14   128.9 2013.87   178.5 2000.42   188.4 1997.88
   198.4 1996.10   208.3 1995.64   218.2 1995.64   232.3 1995.88   247.3 1996.10
   287.6 1995.96   297.6 1996.19   307.5 1997.21   317.4 1999.41   357.1 2010.87
   396.7 2022.08   446.3 2035.72   476.1 2043.55
#Mann= 3 , 0 , 0
       0     0.1       0   232.3   0.045       0   247.3     0.1       0
Bank Sta=   232.3,   247.3
Exp/Cntr=0.3,0.1

Type RM Length L Ch R = 1 ,9691.3,456,457.5,448.4
XS GIS Cut Line= 2
     2121624.343      314745.817     2120930.067      314858.894
#Sta/Elev= 30
       0 2016.41    20.1 2018.99    40.2 2020.92    90.4 2024.34   100.5 2024.50
   130.6 2022.94   170.8 2018.88   180.9 2018.55   221.1 2019.94   241.2 2019.81
   251.2 2019.08   271.3 2016.83   301.5 2011.82   321.6 2007.39   351.7 1999.58
   361.8 1997.29   371.8 1995.78   391.9 1994.71   462.2 1992.66   464.1 1992.68
   479.1 1992.87   532.6 1993.36   542.6 1994.01   552.7 1996.08   602.9 2014.78
   623.0 2021.90   633.1 2025.01   643.1 2027.38   673.3 2033.08   703.4 2039.54
#Mann= 3 , 0 , 0
       0     0.1       0   464.1   0.045       0   479.1     0.1       0
Bank Sta=   464.1,   479.1
Exp/Cntr=0.3,0.1

Type RM Length L Ch R = 1 ,9233.7,556.4,570.1,579.1
XS GIS Cut Line= 2
     2121315.230      314343.682     2120875.184      314616.174
#Sta/Elev= 28
       0 2033.85    79.6 2022.10    89.6 2020.64   119.4 2016.52   129.4 2014.95
   139.4 2012.81   149.3 2010.41   199.1 1998.04   209.0 1995.95   219.0 1994.60
   228.9 1993.89   268.8 1992.14   278.7 1991.86   284.7 1991.83   288.6 1991.82
   299.7 1992.00   358.3 1993.64   368.3 1994.40   378.2 1996.63   388.2 2000.04
   398.1 2003.64   418.0 2010.72   438.0 2017.72   457.9 2024.81   467.8 2028.03
   477.8 2030.57   497.7 2034.48   517.6 2038.75
#Mann= 3 , 0 , 0
       0     0.1       0   284.7   0.045       0   299.7     0.1       0
Bank Sta=   284.7,   299.7
Exp/Cntr=0.3,0.1

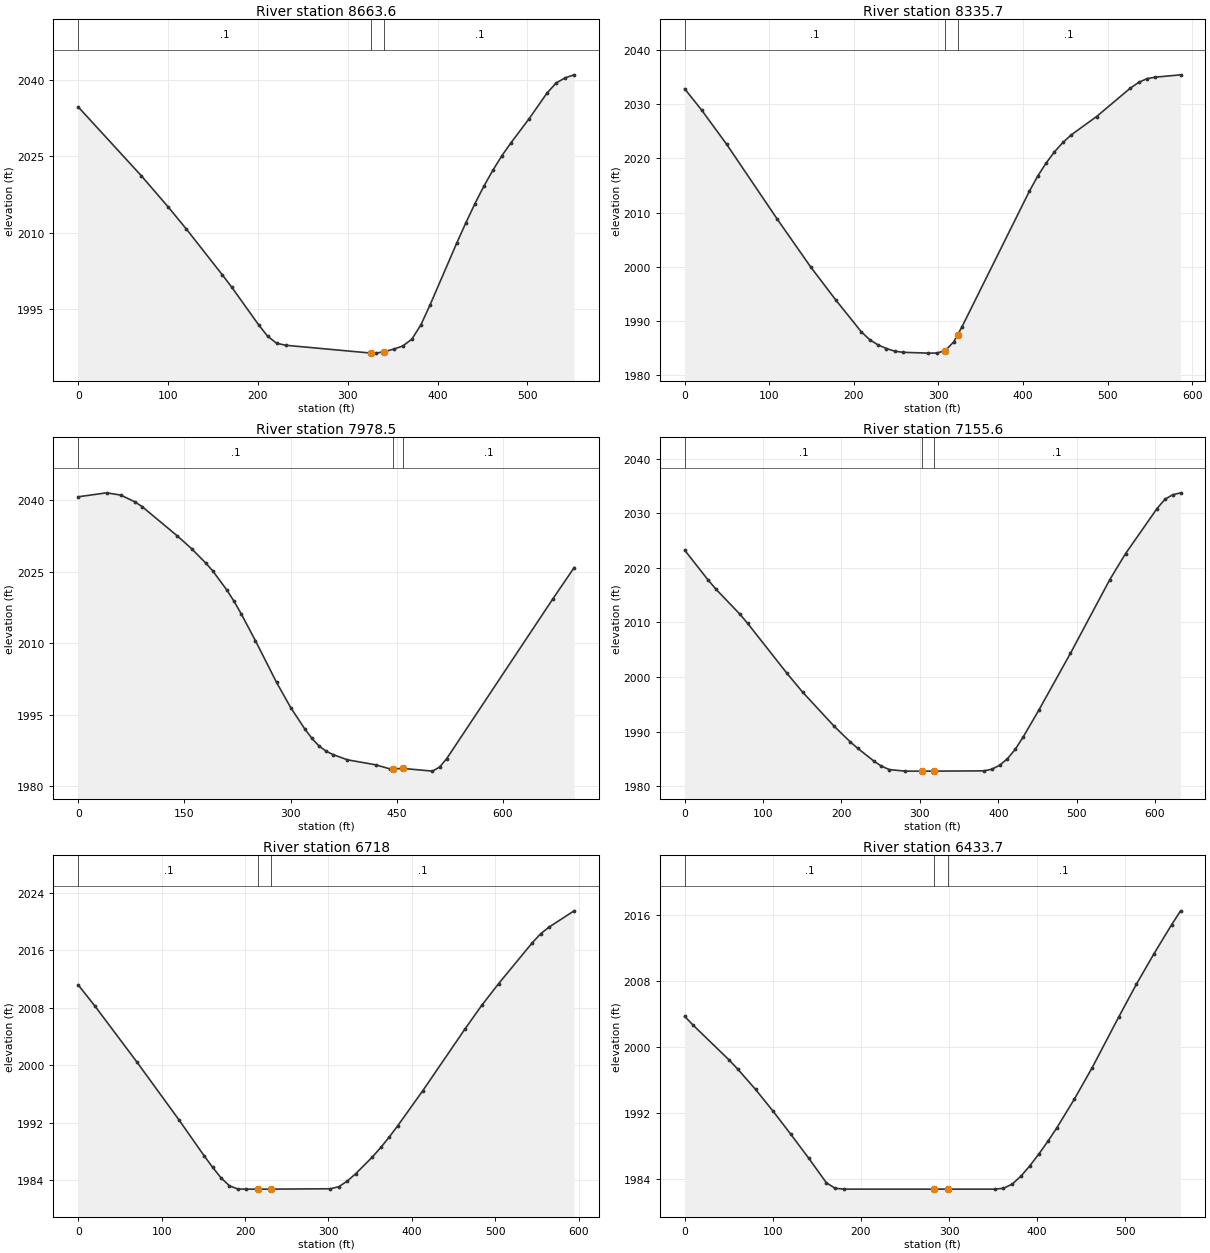
Type RM Length L Ch R = 1 ,8663.6,323.8,327.9,338.6
XS GIS Cut Line= 2
     2121261.564      314031.541     2120712.044      314085.104
#Sta/Elev= 30
       0 2034.73    70.3 2021.18   100.4 2015.01   120.5 2010.69   160.6 2001.67
   170.7 1999.33   200.8 1991.89   210.8 1989.65   220.8 1988.26   230.9 1987.86
   325.8 1986.32   331.3 1986.31   340.8 1986.60   351.4 1987.10   361.4 1987.73
   371.4 1989.05   381.5 1991.88   391.5 1995.72   421.6 2008.04   431.7 2011.99
   441.7 2015.73   451.7 2019.18   461.8 2022.33   471.8 2025.17   481.8 2027.68
   501.9 2032.40   522.0 2037.48   532.0 2039.43   542.1 2040.45   552.1 2041.04
#Mann= 3 , 0 , 0
       0     0.1       0   325.8   0.045       0   340.8     0.1       0
Bank Sta=   325.8,   340.8
Exp/Cntr=0.3,0.1

Type RM Length L Ch R = 1 ,8335.7,347.9,357.2,351.9
XS GIS Cut Line= 2
     2121259.143      313767.656     2120673.175      313749.277
#Sta/Elev= 30
       0 2032.85    19.9 2028.96    49.7 2022.60   109.3 2008.84   149.0 1999.98
   178.9 1993.84   208.7 1988.05   218.6 1986.58   228.5 1985.62   238.5 1984.94
   248.4 1984.45   258.4 1984.24   288.2 1984.09   298.1 1984.11   307.7 1984.53
   318.0 1986.14   322.7 1987.48   327.9 1988.97   407.4 2013.93   417.3 2016.73
   427.3 2019.16   437.2 2021.23   447.1 2022.95   457.1 2024.36   486.9 2027.73
   526.6 2032.94   536.6 2034.03   546.5 2034.72   556.4 2035.00   586.3 2035.43
#Mann= 3 , 0 , 0
       0     0.1       0   307.7   0.045       0   322.7     0.1       0
Bank Sta=   307.7,   322.7
Exp/Cntr=0.3,0.1

Type RM Length L Ch R = 1 ,7978.5,730.3,822.9,893.1
XS GIS Cut Line= 2
     2121217.197      313213.640     2120663.073      313642.193
#Sta/Elev= 30
       0 2040.69    40.0 2041.52    60.0 2041.05    80.1 2039.62    90.1 2038.65
   140.1 2032.48   160.1 2029.83   180.1 2026.82   190.1 2025.15   210.2 2021.10
   220.2 2018.78   230.2 2016.18   250.2 2010.57   280.2 2001.79   300.2 1996.51
   320.2 1992.01   330.2 1990.07   340.2 1988.46   350.2 1987.39   360.3 1986.66
   380.3 1985.58   420.3 1984.53   440.3 1983.68   444.1 1983.68   459.1 1983.77
   500.4 1983.21   510.4 1984.06   520.4 1985.81   670.5 2019.32   700.5 2025.86
#Mann= 3 , 0 , 0
       0     0.1       0   444.1   0.045       0   459.1     0.1       0
Bank Sta=   444.1,   459.1
Exp/Cntr=0.3,0.1

Type RM Length L Ch R = 1 ,7155.6,431.8,437.6,428.1
XS GIS Cut Line= 2
     2120539.738      312938.303     2120440.341      313563.084
#Sta/Elev= 30
       0 2023.24    30.1 2017.74    40.2 2016.05    70.3 2011.54    80.3 2009.84
   130.5 2000.69   150.6 1997.22   190.8 1990.98   210.9 1988.18   220.9 1986.94
   241.0 1984.66   251.0 1983.69   261.1 1983.06   281.2 1982.78   302.7 1982.78
   317.7 1982.78   381.6 1982.83   391.6 1983.12   401.7 1983.85   411.7 1985.05
   421.8 1986.80   431.8 1989.05   451.9 1993.99   492.0 2004.34   542.3 2017.86
   562.4 2022.62   602.5 2030.86   612.6 2032.57   622.6 2033.39   632.6 2033.74
#Mann= 3 , 0 , 0
       0     0.1       0   302.7   0.045       0   317.7     0.1       0
Bank Sta=   302.7,   317.7
Exp/Cntr=0.3,0.1

Type RM Length L Ch R = 1 ,6718,297.2,284.3,265.5
XS GIS Cut Line= 2
     2120309.169      312889.489     2120053.427      313426.413
#Sta/Elev= 28
       0 2011.21    20.2 2008.24    70.6 2000.44   121.0 1992.39   151.2 1987.39
   161.3 1985.80   171.4 1984.33   181.4 1983.24   191.5 1982.79   201.6 1982.78
   216.1 1982.78   231.1 1982.78   302.4 1982.83   312.5 1983.12   322.6 1983.90
   332.6 1984.91   352.8 1987.26   362.9 1988.59   373.0 1990.04   383.0 1991.58
   413.3 1996.50   463.7 2005.06   483.8 2008.35   504.0 2011.37   544.3 2017.05
   554.4 2018.31   564.5 2019.25   594.7 2021.52
#Mann= 3 , 0 , 0
       0     0.1       0   216.1   0.045       0   231.1     0.1       0
Bank Sta=   216.1,   231.1
Exp/Cntr=0.3,0.1

Type RM Length L Ch R = 1 ,6433.7,399.4,417.1,401.7
XS GIS Cut Line= 2
     2119908.061      312834.912     2119967.878      313394.499
#Sta/Elev= 28
       0 2003.74    10.0 2002.63    50.2 1998.47    60.3 1997.33    80.4 1994.88
   100.5 1992.21   120.6 1989.41   140.7 1986.54   160.8 1983.55   170.8 1982.88
   180.9 1982.78   283.3 1982.78   298.3 1982.78   351.7 1982.78   361.8 1982.88
   371.8 1983.40   381.9 1984.39   391.9 1985.64   402.0 1987.05   412.0 1988.56
   422.1 1990.18   442.2 1993.70   462.3 1997.49   492.4 2003.63   512.5 2007.62
   532.6 2011.34   552.7 2014.88   562.8 2016.54
#Mann= 3 , 0 , 0
       0     0.1       0   283.3   0.045       0   298.3     0.1       0
Bank Sta=   283.3,   298.3
Exp/Cntr=0.3,0.1

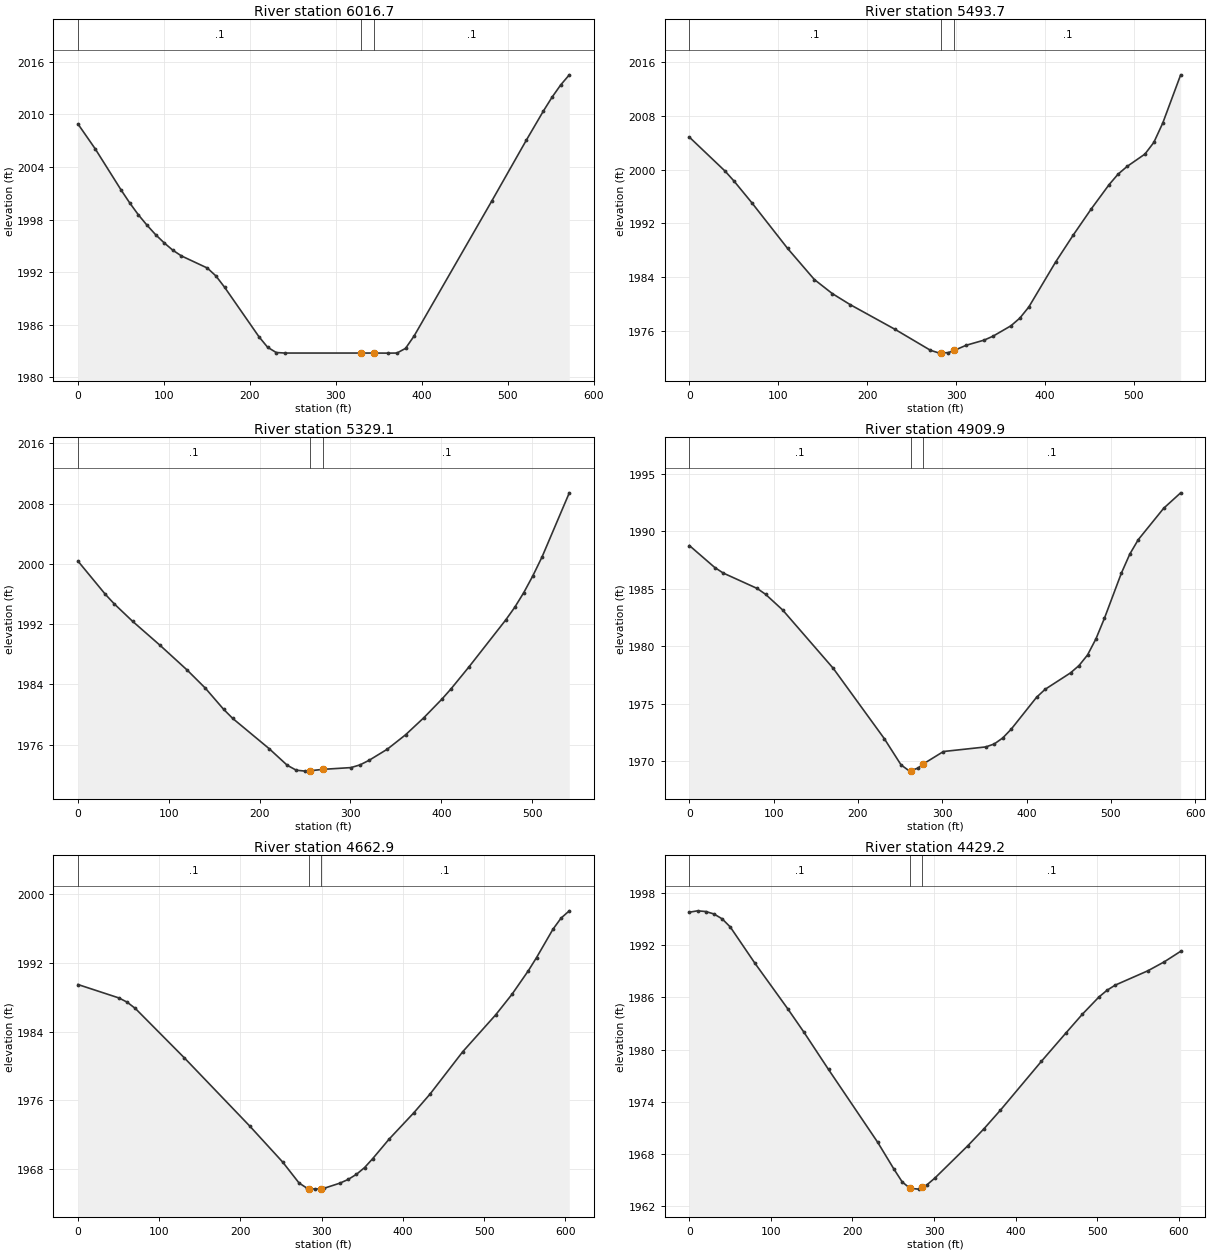
Type RM Length L Ch R = 1 ,6016.7,517,523,528.8
XS GIS Cut Line= 2
     2119471.980      312973.789     2119769.329      313462.228
#Sta/Elev= 29
       0 2008.91    20.1 2006.07    50.2 2001.38    60.2 1999.91    70.2 1998.56
    80.3 1997.37    90.3 1996.29   100.3 1995.35   110.4 1994.51   120.4 1993.86
   150.5 1992.48   160.5 1991.58   170.6 1990.29   210.7 1984.63   220.7 1983.44
   230.7 1982.84   240.8 1982.78   329.3 1982.78   344.3 1982.78   361.2 1982.77
   371.2 1982.78   381.2 1983.31   391.2 1984.73   481.5 2000.11   521.7 2007.05
   541.7 2010.40   551.8 2011.98   561.8 2013.37   571.8 2014.52
#Mann= 3 , 0 , 0
       0     0.1       0   329.3   0.045       0   344.3     0.1       0
Bank Sta=   329.3,   344.3
Exp/Cntr=0.3,0.1

Type RM Length L Ch R = 1 ,5493.7,167.2,164.6,162
XS GIS Cut Line= 2
     2119109.877      313108.090     2119220.478      313649.453
#Sta/Elev= 30
       0 2004.81    40.2 1999.76    50.2 1998.29    70.3 1995.06   110.5 1988.28
   140.6 1983.66   160.7 1981.58   180.8 1979.94   231.1 1976.28   271.2 1973.15
   281.3 1972.73   282.9 1972.74   291.3 1972.81   297.9 1973.13   311.4 1973.90
   331.5 1974.66   341.6 1975.25   361.7 1976.79   371.7 1977.93   381.8 1979.58
   411.9 1986.25   432.0 1990.31   452.1 1994.16   472.2 1997.77   482.2 1999.31
   492.3 2000.45   512.4 2002.29   522.4 2004.02   532.4 2006.88   552.6 2014.06
#Mann= 3 , 0 , 0
       0     0.1       0   282.9   0.045       0   297.9     0.1       0
Bank Sta=   282.9,   297.9
Exp/Cntr=0.3,0.1

Type RM Length L Ch R = 1 ,5329.1,416,419.2,402.1
XS GIS Cut Line= 2
     2118925.085      313176.628     2119093.507      313690.754
#Sta/Elev= 30
       0 2000.36    30.1 1995.96    40.1 1994.67    60.1 1992.38    90.2 1989.21
   120.2 1985.91   140.3 1983.50   160.3 1980.71   170.3 1979.50   210.4 1975.49
   230.4 1973.28   240.4 1972.62   250.5 1972.50   255.3 1972.55   270.3 1972.74
   300.6 1972.97   310.6 1973.33   320.6 1973.94   340.6 1975.41   360.7 1977.32
   380.7 1979.57   400.8 1982.06   410.8 1983.42   430.8 1986.37   470.9 1992.54
   480.9 1994.23   490.9 1996.19   500.9 1998.42   511.0 2000.92   541.0 2009.42
#Mann= 3 , 0 , 0
       0     0.1       0   255.3   0.045       0   270.3     0.1       0
Bank Sta=   255.3,   270.3
Exp/Cntr=0.3,0.1

Type RM Length L Ch R = 1 ,4909.9,226.5,247,250.8
XS GIS Cut Line= 2
     2118614.449      313244.290     2118663.518      313825.126
#Sta/Elev= 30
       0 1988.77    30.2 1986.85    40.2 1986.37    80.4 1985.03    90.4 1984.52
   110.6 1983.16   170.8 1978.06   231.2 1971.95   251.2 1969.65   261.3 1969.11
   262.4 1969.14   271.4 1969.38   277.4 1969.73   301.5 1970.82   351.8 1971.22
   361.8 1971.48   371.8 1972.00   381.9 1972.77   412.0 1975.55   422.1 1976.24
   452.2 1977.67   462.3 1978.31   472.4 1979.23   482.4 1980.64   492.4 1982.42
   512.6 1986.37   522.6 1988.03   532.6 1989.28   562.8 1992.02   582.9 1993.36
#Mann= 3 , 0 , 0
       0     0.1       0   262.4   0.045       0   277.4     0.1       0
Bank Sta=   262.4,   277.4
Exp/Cntr=0.3,0.1

Type RM Length L Ch R = 1 ,4662.9,242.2,233.8,233.5
XS GIS Cut Line= 2
     2118450.310      313233.450     2118396.881      313835.995
#Sta/Elev= 29
       0 1989.47    50.4 1987.91    60.5 1987.42    70.6 1986.69   131.1 1980.93
   211.7 1972.99   252.0 1968.83   272.2 1966.39   282.3 1965.77   283.9 1965.75
   292.4 1965.68   298.9 1965.73   302.4 1965.76   322.6 1966.38   332.7 1966.81
   342.8 1967.40   352.9 1968.19   362.9 1969.23   383.1 1971.50   413.4 1974.55
   433.5 1976.74   473.8 1981.67   514.2 1985.94   534.3 1988.33   554.5 1991.08
   564.6 1992.61   584.7 1995.89   594.8 1997.20   604.9 1998.04
#Mann= 3 , 0 , 0
       0     0.1       0   283.9   0.045       0   298.9     0.1       0
Bank Sta=   283.9,   298.9
Exp/Cntr=0.3,0.1

Type RM Length L Ch R = 1 ,4429.2,297.9,295.9,293.5
XS GIS Cut Line= 2
     2118232.559      313230.365     2118162.343      313828.549
#Sta/Elev= 30
       0 1995.78    10.0 1995.94    20.1 1995.86    30.1 1995.58    40.2 1995.02
    50.2 1994.08    80.3 1989.93   120.5 1984.70   140.5 1981.99   170.6 1977.71
   230.9 1969.34   251.0 1966.23   261.0 1964.78   270.6 1964.05   281.1 1963.96
   285.6 1964.17   291.1 1964.44   301.2 1965.25   341.3 1968.94   361.4 1970.92
   381.4 1973.04   431.6 1978.65   461.8 1981.92   481.8 1984.06   501.9 1986.02
   512.0 1986.81   522.0 1987.40   562.1 1989.05   582.2 1990.08   602.3 1991.29
#Mann= 3 , 0 , 0
       0     0.1       0   270.6   0.045       0   285.6     0.1       0
Bank Sta=   270.6,   285.6
Exp/Cntr=0.3,0.1

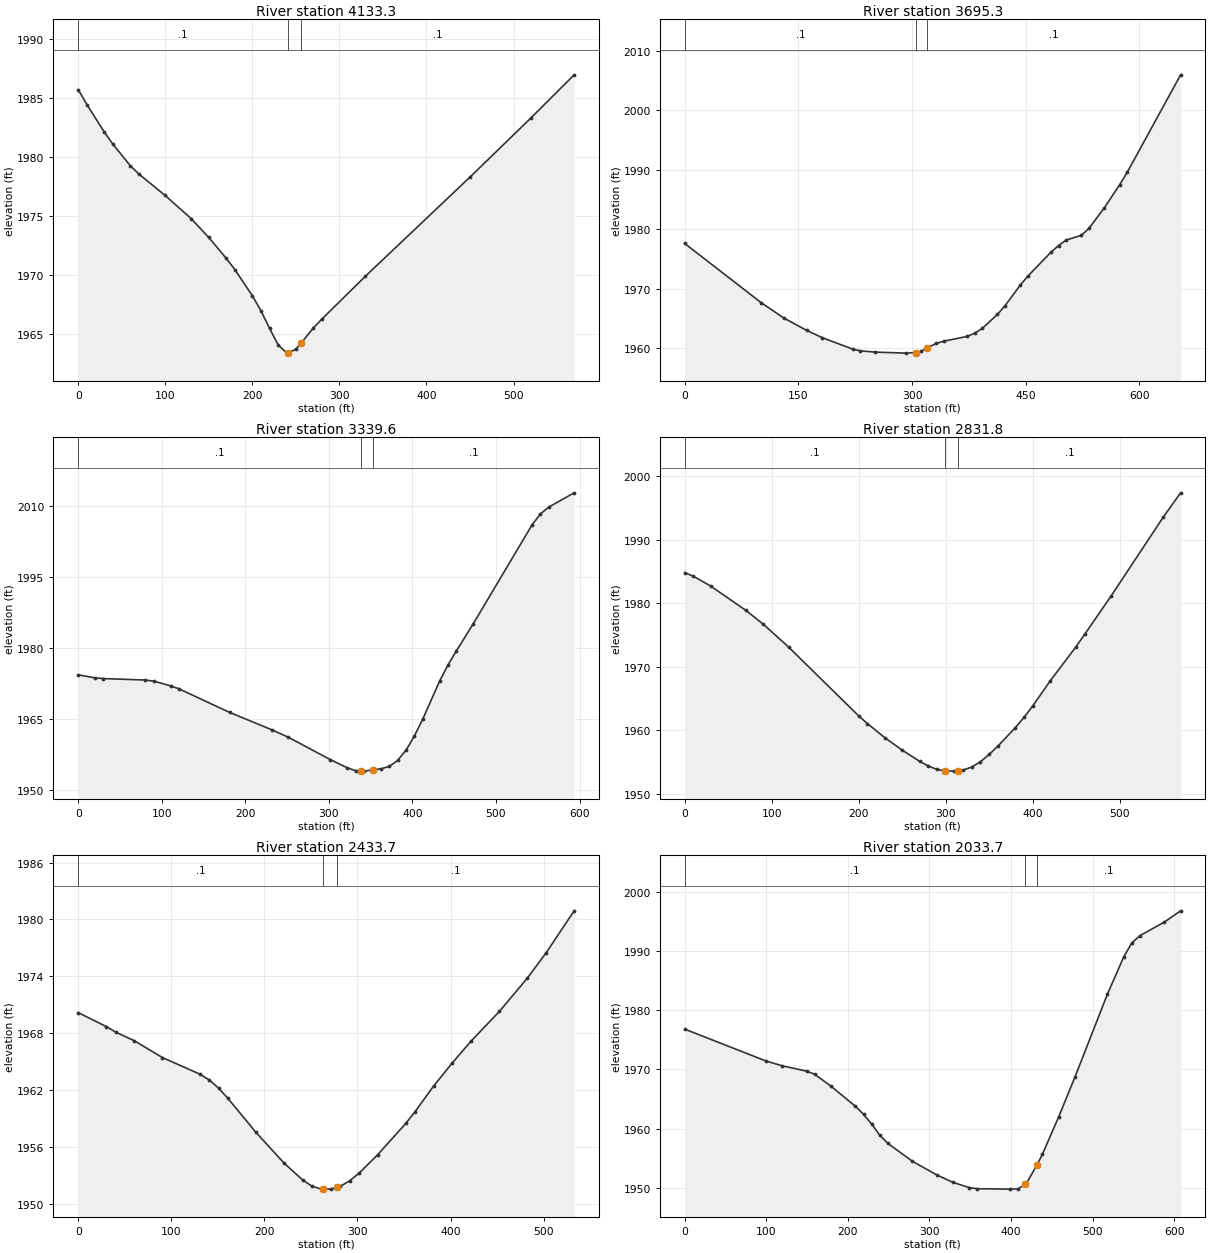
Type RM Length L Ch R = 1 ,4133.3,442.4,438,433.2
XS GIS Cut Line= 2
     2117941.376      313251.671     2117916.451      313820.743
#Sta/Elev= 25
       0 1985.70    10.0 1984.43    30.0 1982.10    40.0 1981.06    60.0 1979.24
    70.0 1978.53    99.9 1976.73   129.9 1974.76   149.9 1973.18   169.9 1971.42
   179.9 1970.46   199.9 1968.25   209.9 1966.97   219.8 1965.47   229.8 1964.06
   239.8 1963.38   241.1 1963.42   249.8 1963.69   256.1 1964.24   269.8 1965.48
   279.8 1966.26   329.8 1969.89   449.7 1978.27   519.6 1983.27   569.6 1986.95
#Mann= 3 , 0 , 0
       0     0.1       0   241.1   0.045       0   256.1     0.1       0
Bank Sta=   241.1,   256.1
Exp/Cntr=0.3,0.1

Type RM Length L Ch R = 1 ,3695.3,343.6,355.7,367.8
XS GIS Cut Line= 2
     2117470.930      313286.094     2117577.538      313931.809
#Sta/Elev= 30
       0 1977.60   100.7 1967.68   130.9 1965.07   161.1 1962.99   181.2 1961.80
   221.5 1959.86   231.6 1959.57   251.7 1959.35   292.0 1959.18   305.1 1959.27
   312.1 1959.48   320.1 1960.07   332.3 1960.82   342.3 1961.19   372.5 1961.98
   382.6 1962.51   392.7 1963.33   412.8 1965.69   422.9 1967.16   443.0 1970.62
   453.1 1972.14   483.3 1976.12   493.4 1977.25   503.4 1978.17   523.6 1978.97
   533.6 1980.14   553.8 1983.58   573.9 1987.43   584.0 1989.54   654.5 2005.92
#Mann= 3 , 0 , 0
       0     0.1       0   305.1   0.045       0   320.1     0.1       0
Bank Sta=   305.1,   320.1
Exp/Cntr=0.3,0.1

Type RM Length L Ch R = 1 ,3339.6,449.9,507.8,433
XS GIS Cut Line= 2
     2117294.091      313274.367     2117108.902      313838.326
#Sta/Elev= 30
       0 1974.40    20.1 1973.75    30.2 1973.60    80.5 1973.29    90.6 1973.06
   110.7 1972.05   120.7 1971.43   181.1 1966.46   231.4 1962.80   251.5 1961.20
   301.8 1956.47   322.0 1954.75   332.0 1954.14   337.9 1954.08   342.1 1954.04
   352.9 1954.31   362.2 1954.53   372.2 1955.02   382.3 1956.30   392.4 1958.49
   402.4 1961.47   412.5 1965.08   432.6 1973.07   442.7 1976.51   452.7 1979.47
   472.9 1985.20   543.3 2006.11   553.3 2008.41   563.4 2009.86   593.6 2012.86
#Mann= 3 , 0 , 0
       0     0.1       0   337.9   0.045       0   352.9     0.1       0
Bank Sta=   337.9,   352.9
Exp/Cntr=0.3,0.1

Type RM Length L Ch R = 1 ,2831.8,363,398.1,416.9
XS GIS Cut Line= 2
     2116932.346      313171.599     2116791.877      313724.197
#Sta/Elev= 30
       0 1984.80    10.0 1984.23    30.0 1982.68    70.0 1978.90    90.0 1976.74
   120.0 1973.03   200.1 1962.27   210.1 1961.07   230.1 1958.85   250.1 1956.89
   270.1 1955.14   280.1 1954.40   290.1 1953.85   299.3 1953.64   310.1 1953.59
   314.3 1953.66   320.1 1953.76   330.1 1954.23   340.1 1955.07   350.1 1956.22
   360.1 1957.52   380.1 1960.42   390.1 1962.03   400.1 1963.83   420.1 1967.75
   450.1 1973.18   460.1 1975.14   490.2 1981.11   550.2 1993.52   570.2 1997.35
#Mann= 3 , 0 , 0
       0     0.1       0   299.3   0.045       0   314.3     0.1       0
Bank Sta=   299.3,   314.3
Exp/Cntr=0.3,0.1

Type RM Length L Ch R = 1 ,2433.7,321.8,400,383.7
XS GIS Cut Line= 2
     2116653.257      313118.097     2116496.598      313627.368
#Sta/Elev= 30
       0 1970.17    30.2 1968.70    40.2 1968.12    60.3 1967.20    90.5 1965.43
   130.7 1963.68   140.8 1963.07   150.8 1962.20   160.8 1961.13   191.0 1957.53
   221.2 1954.29   241.3 1952.50   251.3 1951.85   261.4 1951.55     263 1951.55
   271.4 1951.56     278 1951.74   281.5 1951.84   291.5 1952.42   301.6 1953.22
   321.7 1955.18   351.9 1958.48   361.9 1959.72   382.0 1962.45   402.1 1964.89
   422.2 1967.18   452.4 1970.29   482.6 1973.82   502.7 1976.48   532.8 1980.91
#Mann= 3 , 0 , 0
       0     0.1       0     263   0.045       0     278     0.1       0
Bank Sta=     263,     278
Exp/Cntr=0.3,0.1

Type RM Length L Ch R = 1 ,2033.7,424.7,389.5,383
XS GIS Cut Line= 2
     2116532.065      313034.572     2116149.495      313506.872
#Sta/Elev= 30
       0 1976.83    99.6 1971.44   119.6 1970.62   149.5 1969.72   159.4 1969.19
   179.4 1967.16   209.2 1963.78   219.2 1962.42   229.2 1960.77   239.1 1958.87
   249.1 1957.49   279.0 1954.48   308.9 1952.17   328.8 1950.90   348.7 1950.02
   358.7 1949.83   398.6 1949.76   408.5 1949.80   417.1 1950.55   418.5 1950.67
   432.1 1953.92   438.4 1955.66   458.3 1961.96   478.3 1968.72   518.1 1982.75
   538.1 1989.05   548.0 1991.41   558.0 1992.64   587.9 1994.94   607.8 1996.84
#Mann= 3 , 0 , 0
       0     0.1       0   417.1   0.045       0   432.1     0.1       0
Bank Sta=   417.1,   432.1
Exp/Cntr=0.3,0.1