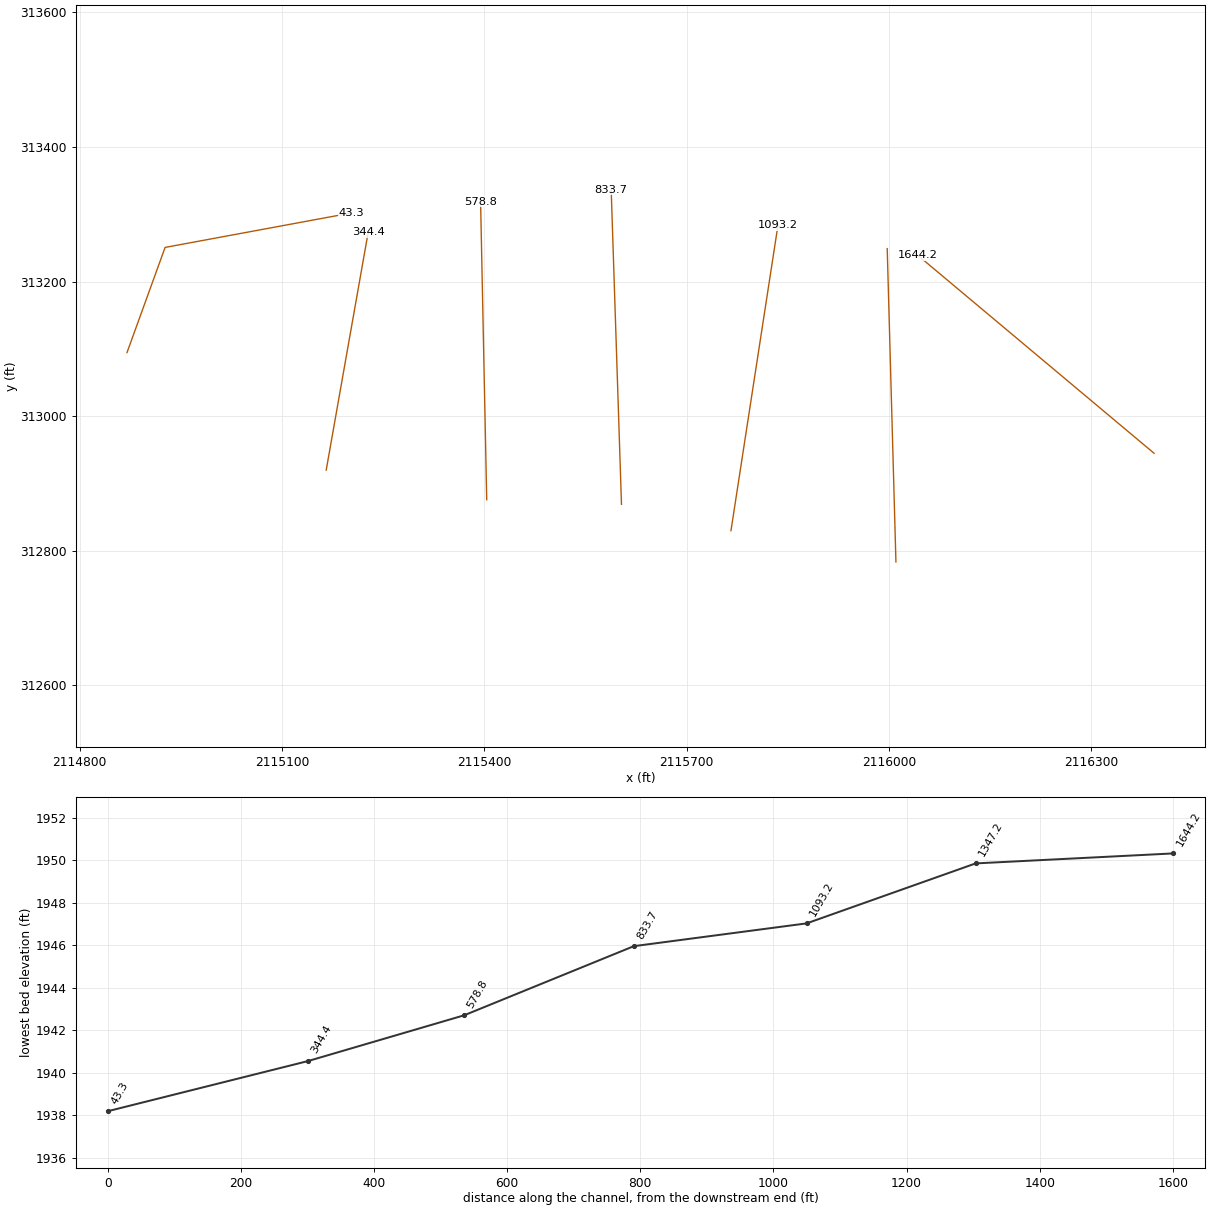
HEC-RAS study MlgnCkT3.prj: MlgnCkT3

--- MlgnCkT3.g01 (geometry) --- (continued)

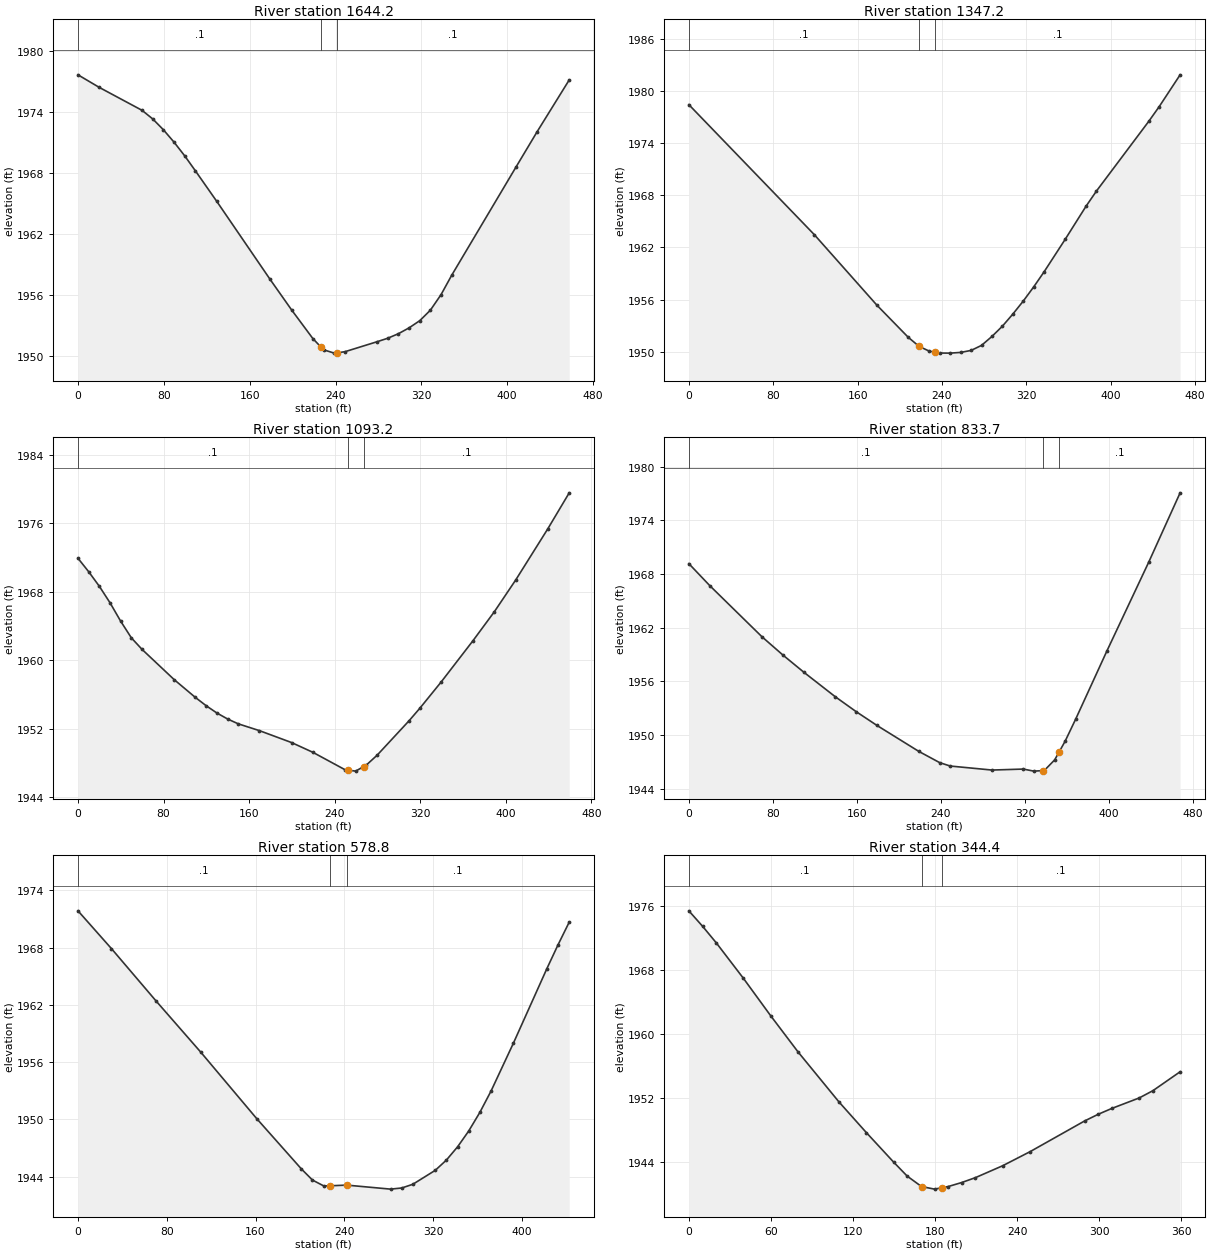
Type RM Length L Ch R = 1 ,1644.2,318.5,297.1,286.6
XS GIS Cut Line= 2
     2116392.964      312944.802     2116042.371      313239.182
#Sta/Elev= 28
       0 1977.68    19.9 1976.44    59.7 1974.19    69.7 1973.34    79.6 1972.28
    89.6 1971.05    99.5 1969.71   109.5 1968.23   129.4 1965.23   179.1 1957.56
   199.0 1954.58   218.9 1951.75   226.4 1950.92   228.9 1950.65   238.8 1950.32
   241.4 1950.35   248.8 1950.46   278.7 1951.44   288.6 1951.78   298.6 1952.23
   308.5 1952.80   318.5 1953.51   328.4 1954.54   338.4 1956.08   348.3 1957.98
   408.0 1968.58   427.9 1972.09   457.8 1977.18
#Mann= 3 , 0 , 0
       0     0.1       0   226.4   0.045       0   241.4     0.1       0
Bank Sta=   226.4,   241.4
Exp/Cntr=0.3,0.1

Type RM Length L Ch R = 1 ,1347.2,258,254,234.5
XS GIS Cut Line= 2
     2116010.244      312783.287     2115997.311      313248.864
#Sta/Elev= 24
       0 1978.42   118.9 1963.48   178.4 1955.35   208.1 1951.66   218.3 1950.63
   227.9 1950.08   233.3 1949.96   237.8 1949.86   247.7 1949.85   257.6 1949.93
   267.6 1950.16   277.5 1950.74   287.4 1951.77   297.3 1952.95   307.2 1954.34
   317.1 1955.84   327.0 1957.47   336.9 1959.21   356.8 1962.93   376.6 1966.74
   386.5 1968.49   436.0 1976.49   445.9 1978.18   465.8 1981.85
#Mann= 3 , 0 , 0
       0     0.1       0   218.3   0.045       0   233.3     0.1       0
Bank Sta=   218.3,   233.3
Exp/Cntr=0.3,0.1

Type RM Length L Ch R = 1 ,1093.2,255.5,259.4,263.4
XS GIS Cut Line= 2
     2115765.638      312829.719     2115835.341      313283.668
#Sta/Elev= 30
       0 1971.91    10.0 1970.34    20.0 1968.63    30.0 1966.70    39.9 1964.56
    49.9 1962.61    59.9 1961.26    89.9 1957.73   109.8 1955.64   119.8 1954.68
   129.8 1953.83   139.8 1953.13   149.8 1952.56   169.7 1951.76   199.7 1950.37
   219.6 1949.23   249.6 1947.20   252.1 1947.16   259.6 1947.03   267.1 1947.56
   269.6 1947.74   279.6 1948.88   309.5 1952.91   319.5 1954.36   339.5 1957.44
   369.4 1962.29   389.4 1965.68   409.4 1969.40   439.3 1975.36   459.3 1979.56
#Mann= 3 , 0 , 0
       0     0.1       0   252.1   0.045       0   267.1     0.1       0
Bank Sta=   252.1,   267.1
Exp/Cntr=0.3,0.1

Type RM Length L Ch R = 1 ,833.7,252.2,254.9,256.6
XS GIS Cut Line= 2
     2115603.324      312868.936     2115588.054      313336.349
#Sta/Elev= 23
       0 1969.17    19.9 1966.71    69.6 1960.99    89.6 1958.94   109.4 1957.03
   139.3 1954.29   159.2 1952.62   179.1 1951.07   218.9 1948.17   238.8 1946.91
   248.8 1946.53   288.6 1946.08   318.4 1946.19   328.4 1945.96   337.4 1946.02
   338.3 1946.02   348.3 1947.22   352.4 1948.08   358.2 1949.30   368.2 1951.76
   398.0 1959.40   437.8 1969.33   467.7 1977.09
#Mann= 3 , 0 , 0
       0     0.1       0   337.4   0.045       0   352.4     0.1       0
Bank Sta=   337.4,   352.4
Exp/Cntr=0.3,0.1

Type RM Length L Ch R = 1 ,578.8,238.9,234.4,227.8
XS GIS Cut Line= 2
     2115403.512      312875.819     2115394.423      313318.420
#Sta/Elev= 23
       0 1971.84    30.2 1967.88    70.4 1962.40   110.7 1957.04   161.0 1950.10
   201.2 1944.84   211.3 1943.66   221.4 1943.05   227.2 1943.06   242.2 1943.13
   281.7 1942.71   291.8 1942.83   301.8 1943.22   322.0 1944.68   332.0 1945.75
   342.1 1947.14   352.1 1948.79   362.2 1950.75   372.3 1952.99   392.4 1957.99
   422.6 1965.80   432.6 1968.28   442.7 1970.66
#Mann= 3 , 0 , 0
       0     0.1       0   227.2   0.045       0   242.2     0.1       0
Bank Sta=   227.2,   242.2
Exp/Cntr=0.3,0.1

Type RM Length L Ch R = 1 ,344.4,341.9,301.1,266.4
XS GIS Cut Line= 2
     2115165.521      312919.804     2115227.824      313273.486
#Sta/Elev= 24
       0 1975.42    10.0 1973.49    20.0 1971.42    39.9 1966.96    59.8 1962.28
    79.8 1957.75   109.7 1951.49   129.7 1947.65   149.6 1943.96   159.6 1942.19
   170.1 1940.88   179.6 1940.56   185.1 1940.74   189.5 1940.88   199.5 1941.39
   209.5 1942.00   229.4 1943.49   249.4 1945.25   289.3 1949.10   299.3 1949.94
   309.2 1950.67   329.2 1951.98   339.2 1952.89   359.1 1955.26
#Mann= 3 , 0 , 0
       0     0.1       0   170.1   0.045       0   185.1     0.1       0
Bank Sta=   170.1,   185.1
Exp/Cntr=0.3,0.1

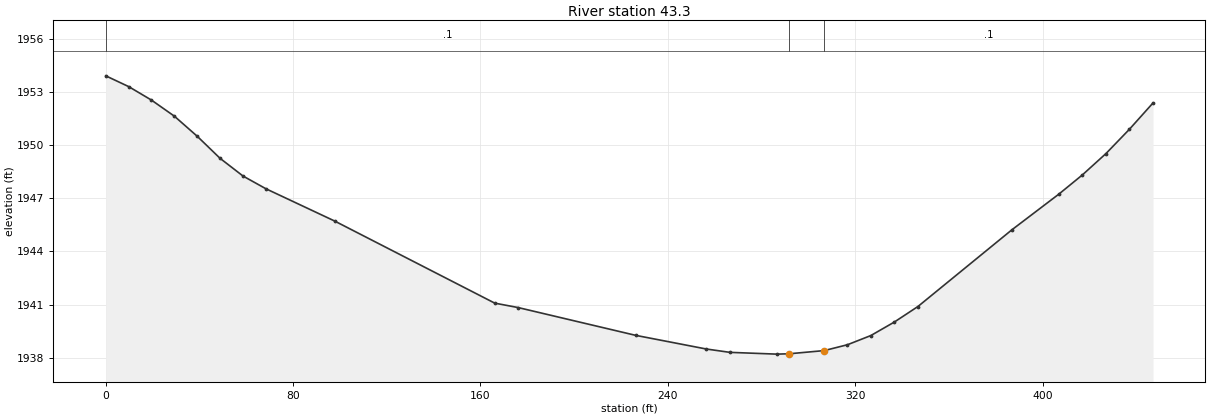
Type RM Length L Ch R = 1 ,43.3,43.9,43.3,42.9
XS GIS Cut Line= 3
     2114870.191      313094.461     2114926.643      313250.666
     2115202.986      313301.907
#Sta/Elev= 27
       0 1953.92     9.8 1953.31    19.5 1952.55    29.3 1951.64    39.1 1950.50
    48.8 1949.26    58.6 1948.26    68.4 1947.54    97.7 1945.72   166.1 1941.08
   176.1 1940.83   226.3 1939.26   256.4 1938.49   266.5 1938.30   286.5 1938.20
   291.8 1938.22   306.8 1938.40   316.7 1938.73   326.7 1939.25   336.7 1940.01
   346.8 1940.89   386.9 1945.22   407.0 1947.24   417.0 1948.32   427.1 1949.53
   437.1 1950.90   447.2 1952.39
#Mann= 3 , 0 , 0
       0     0.1       0   291.8   0.045       0   306.8     0.1       0
Bank Sta=   291.8,   306.8
Exp/Cntr=0.3,0.1